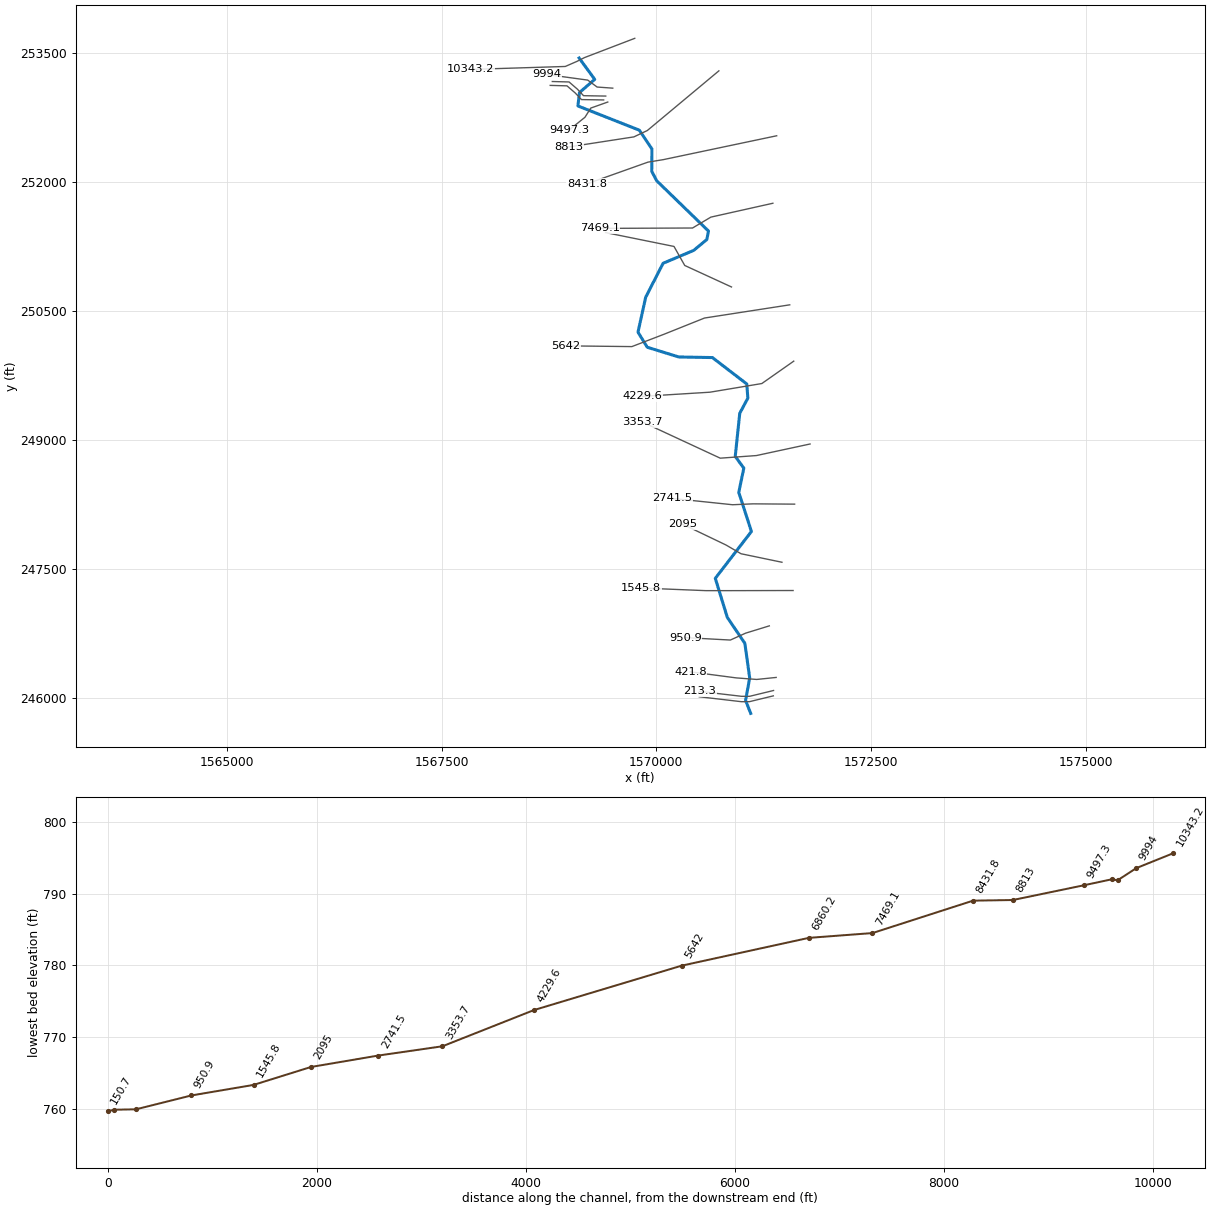
--- WHTKCR.prj (project) ---

Proj Title=WHTKCR
Current Plan=p01
Default Exp/Contr=0,0
English Units
Geom File=g01
Flow File=f01
Plan File=p01
BEGIN DESCRIPTION:
END DESCRIPTION:
DSS Export Rating Curves= 0
DSS Export Rating Curve Sorted= 0
DSS Export Volume Flow Curves= 0
DXF OffsetX= 0
DXF OffsetY= 0
DXF ScaleX= 0
DXF ScaleY= 0

--- WHTKCR.p01 (plan) ---

Plan Title=Floodplain
Program Version=4.00
Geom File=g01
Flow File=f01
K Sum by GR=0
Std Step Tol=0.01
Critical Tol=0.01
Num of Std Step Trials=20
Max Error Tol=0.3
Flow Tol Ratio=0.001
Split Flow NTrial=30
Split Flow Tol=0.02
Split Flow Ratio=0.02
Log Output Level=0
Friction Slope Method=1
Unsteady Friction Slope Method=2
Unsteady Bridges Friction Slope Method=1
Global Log Level=0
CheckData=False
Run HTab=0
Run UNet=0
Run PostProcess=0
UNET Theta=0
UNET Theta Warmup=0
UNET ZTol=0
UNET ZSATol=0
UNET MxIter=0
UNET MaxInSteps=0
UNET DtIC=0
UNET DtMin=0
UNET MaxCRTS=0
UNET WFStab=0
UNET SFStab=0
UNET WFX=0
UNET SFX=0
UNET DSS MLevel=0
UNET DZMax Abort=0
UNET Convert EG Bridges=0
UNET Use Existing IB Tables=0
UNET Froude Limit=0
UNET Froude Power=0
Write IC File=0
Echo Input=False
Echo Output=False
Write Detailed=0

--- WHTKCR.f01 (steady flow) ---

Flow Title=NFF Regression Equation
Program Version=4.10
Number of Profiles= 1
Profile Names=P100yr
River Rch & RM=WHTKCR,Main            ,10343.2
1787.475
River Rch & RM=WHTKCR,Main            ,8813
1822.061
River Rch & RM=WHTKCR,Main            ,8431.8
 2155.74
River Rch & RM=WHTKCR,Main            ,421.8
2301.475
Boundary for River Rch & Prof#=WHTKCR,Main            , 1
Up Type= 0
Dn Type= 3
Dn Slope=0.0026
DSS Import GetInterval= 0
DSS Import GetPeak= 0
DSS Import FillOption= 0

--- WHTKCR.g01 (geometry) ---

Geom Title=USGS 10m DEM
Program Version=4.10

River Reach=WHTKCR          ,Main
Reach XY= 30
     1569101.146      253440.129     1569282.824      253191.552
      1569105.06      253038.257     1569087.076      252882.456
     1569802.073      252600.609     1569948.736      252382.202
     1569946.705      252121.973     1570003.973      252012.626
     1570607.046       251427.41     1570587.628      251328.299
      1570434.14      251202.095     1570078.622      251052.541
      1569876.26      250657.753     1569786.394       250251.61
     1569894.258      250076.005     1570260.925       249962.81
      1570652.73      249955.817      1571053.07      249648.514
     1571064.989       249483.39     1570970.844      249307.526
     1570918.564       248806.56     1571018.344      248669.142
     1570959.536       248387.81     1571106.865      247933.146
     1570686.339       247388.17     1570826.304      246933.246
     1571030.518       246632.06     1571086.648      246229.374
     1571038.703      245968.019     1571098.455       245817.26

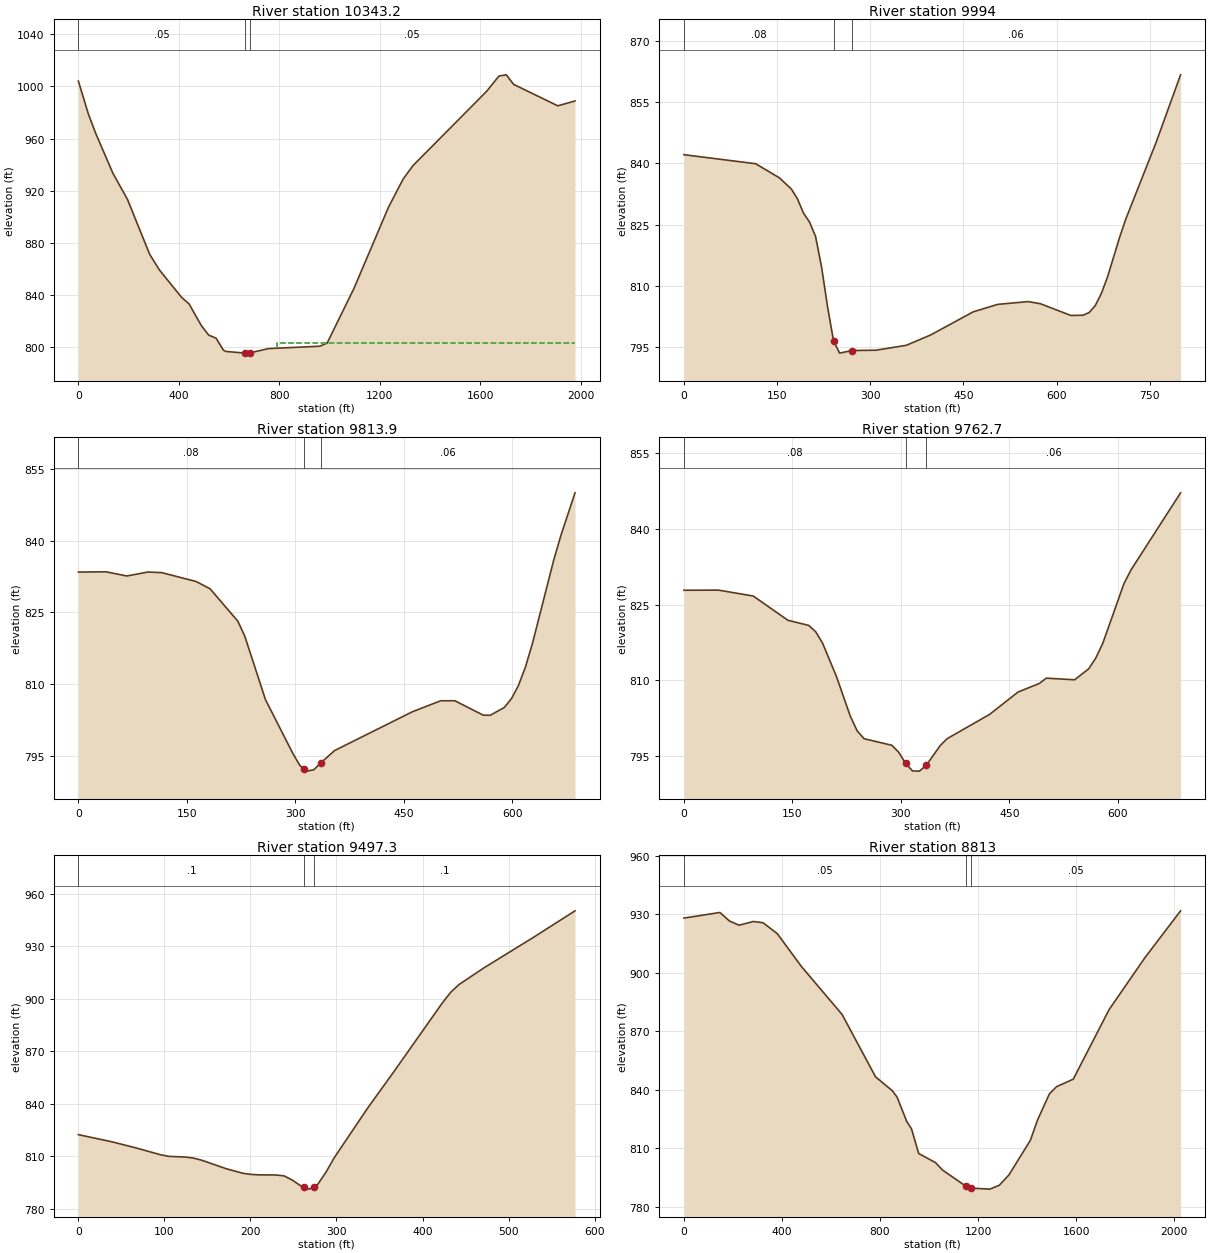
Type RM Length L Ch R = 1 ,10343.2 ,373,349.3,325.5
XS GIS Cut Line= 5
     1569748.891      253668.969     1569163.822       253445.01
     1569073.544      253399.872     1568939.997      253341.756
     1567836.602       253307.38
#Sta/Elev= 30
       0 1004.11    39.2  979.24    68.5  964.25     137  933.65   195.8  913.29
   283.9  871.33     323  859.27   411.1   838.3   440.5  833.37   489.4  816.78
   518.8  809.41   548.2  807.09   577.5  797.87   587.3  796.91   663.2  795.63
   672.4  795.62   681.5  795.75   756.5  799.08     961  800.92   990.3   803.3
  1097.7  845.48  1234.5   907.4  1293.1  929.08  1332.2  939.33  1625.3  996.25
  1674.1 1007.92  1703.4 1008.87  1732.7 1001.55  1908.6  985.11    1977  988.85
#Mann= 3 , 0 , 0
       0     .05       0   663.2    .045       0   681.5     .05       0
#XS Ineff= 2 , 0
                          792.31          803.71
Permanent Ineff=
       F       F
Bank Sta=663.2,681.5
XS Rating Curve= 0 ,0
Exp/Cntr=0.3,0.1

Type RM Length L Ch R = 1 ,9994    ,184.1,180.1,175.9
XS GIS Cut Line= 4
     1569492.852      253089.498     1569310.561      253102.519
     1569201.186      253183.248     1568724.623      253248.352
#Sta/Elev= 30
       0  842.08   115.4  839.88   153.9  836.41   173.1  833.66   182.8   831.3
   192.5   827.8   202.2  825.62   211.9  822.13   221.6  814.62   231.3  804.86
   240.9  796.56   250.7  793.57   270.2  794.21     309  794.28     358  795.48
   397.2  798.01   465.9  803.67   505.2  805.49   554.3  806.17   573.9  805.65
     623  802.78   642.6  802.83   652.4  803.48   662.3  805.19   672.1  808.15
   681.9  812.11   701.5  821.87   711.3  826.27   760.4  845.13   799.7  861.61
#Mann= 3 , 0 , 0
       0     .08       0   240.9    .045       0   270.2     .06       0
Bank Sta=240.9,270.2
XS Rating Curve= 0 ,0
Exp/Cntr=0.3,0.1

Type RM Length L Ch R = 1 ,9813.9  ,52,51.2,50.9
XS GIS Cut Line= 5
     1569411.255      252997.484     1569152.574      253001.825
     1569080.526      253078.214     1568984.172      253161.547
     1568788.859      253166.755
#Sta/Elev= 30
       0  833.44    38.3  833.49    67.1  832.62    95.8  833.44     115  833.33
   162.9  831.46   182.1  829.94   220.4  823.19     230  820.07   258.7  806.77
   296.9  795.43   306.4     793   312.1  792.32     316  791.86   325.5  792.15
   335.1  793.58   354.2  796.16   461.7  804.26   500.9  806.56   520.4  806.56
   559.5  803.56   569.3  803.52   588.8  805.16   598.6  806.98   608.3  809.74
   618.1  813.65   627.9  818.66   657.2  836.01     667  841.08   686.5  849.99
#Mann= 3 , 0 , 0
       0     .08       0   312.1    .045       0   335.1     .06       0
Bank Sta=312.1,335.1
XS Rating Curve= 0 ,0
Exp/Cntr=0.3,0.1

Type RM Length L Ch R = 1 ,9762.7  ,223.1,265.5,306.8
XS GIS Cut Line= 5
     1569386.949      252952.345     1569128.269      252956.686
      1569056.22      253033.075     1568959.866      253116.408
     1568764.554      253121.616
#Sta/Elev= 30
       0  827.86    47.9  827.88    95.8  826.71   143.7  821.91   172.5  820.89
   182.1  819.64   191.6  817.39   210.8  810.77     230  802.89   239.6  799.96
   249.1  798.44   287.4  797.14   296.9  795.76   306.4  793.55     316  792.06
   325.5  792.02   335.1   793.2   354.2  797.08   363.7  798.44   422.5  803.26
   461.7  807.68   491.1  809.38   500.9  810.44     540  810.12   559.5  812.29
   569.3  814.43     579  817.36   608.3   829.2   618.1  831.92   686.5  847.16
#Mann= 3 , 0 , 0
       0     .08       0   306.4    .045       0   335.1     .06       0
Bank Sta=306.4,335.1
XS Rating Curve= 0 ,0
Exp/Cntr=0.3,0.1

Type RM Length L Ch R = 1 ,9497.3  ,697.2,684.3,671.3
XS GIS Cut Line= 4
     1569434.742      252928.029     1569236.826      252857.716
     1569169.117      252750.946     1568981.617      252599.904
#Sta/Elev= 30
       0  822.36    38.2  818.35    66.8  814.79    95.5  810.85     105  809.94
   124.1  809.54   133.7  808.96   143.2  807.75   171.8  802.87   190.9   800.3
   200.5  799.62     210  799.34   229.5  799.29   239.2  798.76   248.9  796.28
   258.7  792.99   262.6  792.27   268.4  791.19   273.3792.5162   278.1  793.82
   287.8   800.9   297.6  809.32   336.5  837.76   365.4  857.46   423.1  897.75
   432.8   903.8   442.4   908.2   471.3  917.72   529.1  935.24   577.2  950.36
#Mann= 3 , 0 , 0
       0      .1       0   262.6    .045       0   273.3      .1       0
Bank Sta=262.6,273.3
XS Rating Curve= 0 ,0
Exp/Cntr=0.3,0.1

Type RM Length L Ch R = 1 ,8813    ,386.9,381.2,375.1
XS GIS Cut Line= 4
     1570728.095      253290.887     1569894.762      252596.443
     1569738.512      252522.658     1568978.963       252405.47
#Sta/Elev= 30
       0  928.06   146.6  930.93   185.7  926.57   224.8  924.41   283.4  926.31
   322.5  925.69   381.1  920.05   478.9   903.3     645  878.67   781.8  846.67
   850.2  839.56   869.8  836.23   908.8  823.84   928.4  819.99   957.7  807.38
  1026.1  802.72  1055.4  798.85    1152  790.47  1171.2  789.65    1248  789.12
  1286.7  791.13  1325.6  796.36  1413.2  814.13  1442.4  824.52    1491  837.96
  1520.2  841.65  1588.3  845.48  1734.2  881.08  1880.2  907.69  2026.1  931.78
#Mann= 3 , 0 , 0
       0     .05       0    1152    .045       0  1171.2     .05       0
Bank Sta=1152,1171.2
XS Rating Curve= 0 ,0
Exp/Cntr=0.3,0.1

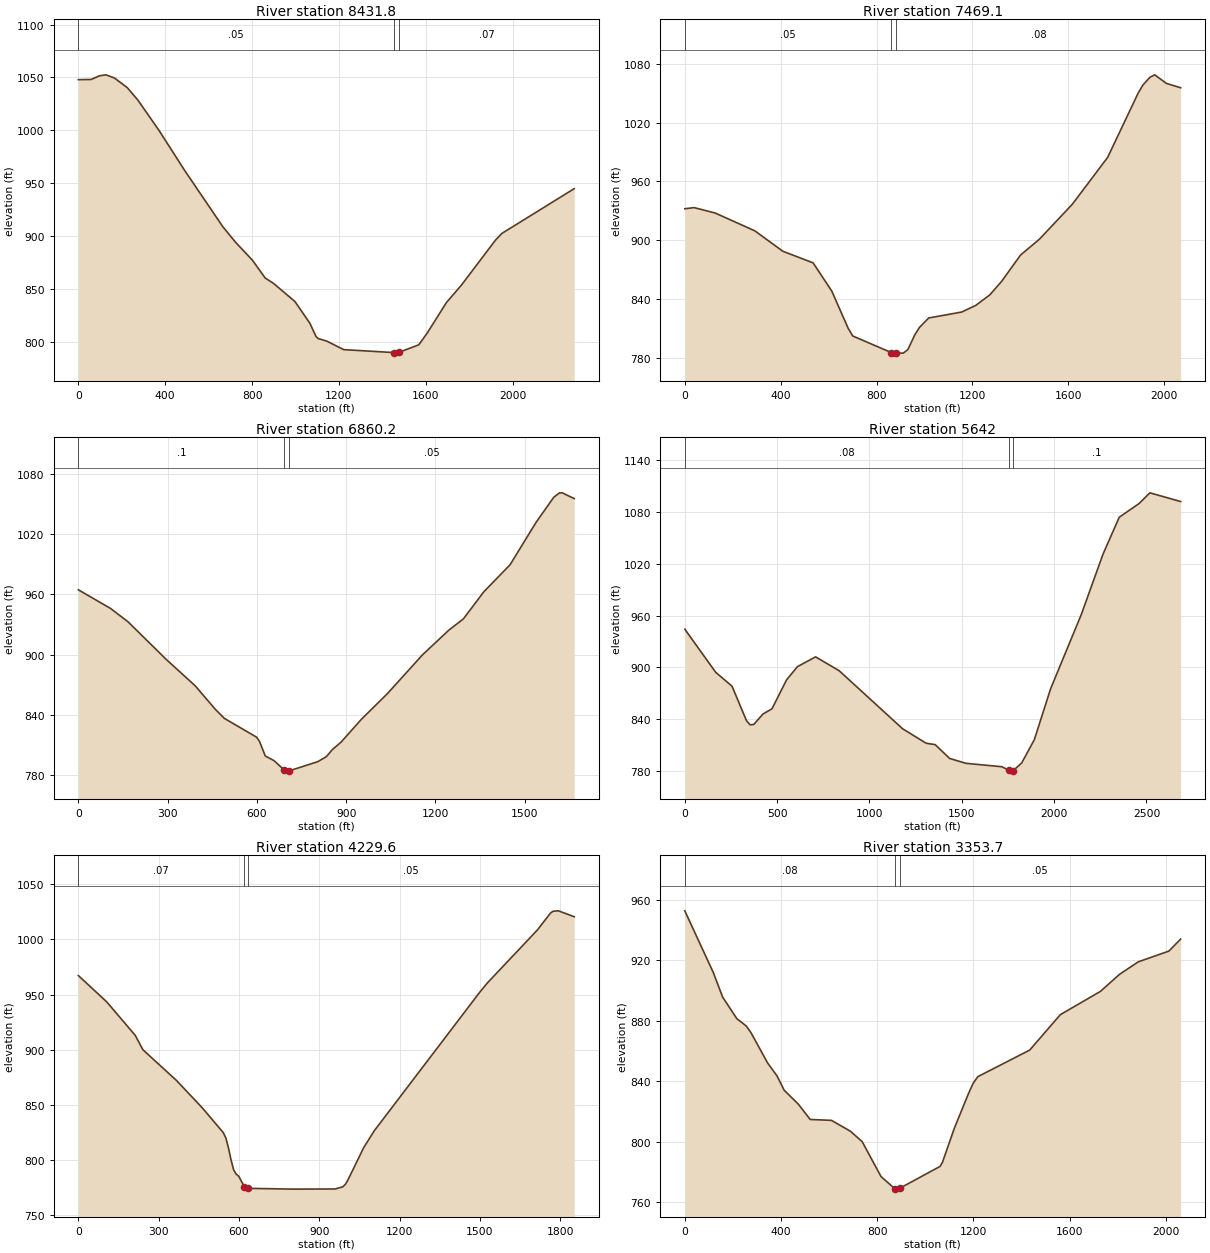
Type RM Length L Ch R = 1 ,8431.8  ,954.5,962.7,970.7
XS GIS Cut Line= 4
     1571400.838      252535.679     1570080.526      252257.901
     1569903.443      252229.255     1569192.505      251976.651
#Sta/Elev= 30
       0 1047.81    58.7 1047.97    97.8 1051.45   127.1 1052.38   166.2 1049.39
   224.9 1040.33   273.8  1028.6   371.5   999.8   488.8  962.15   664.8  908.82
   723.5  894.05   801.7  876.96   860.4  860.14   899.5  854.91   997.2   837.9
  1065.7  817.48    1095   804.6  1104.8   802.8  1143.9  800.42  1222.1  792.33
  1453.1  789.56  1462.5  789.03 1477.42 789.869  1567.8  796.91    1607  808.18
  1695.2  836.95  1763.8  853.32  1920.5  895.88  1949.9  902.26  2283.1  944.63
#Mann= 3 , 0 , 0
       0     .05       0  1453.1    .045       0 1477.42     .07       0
Bank Sta=1453.1,1477.42
XS Rating Curve= 0 ,0
Exp/Cntr=0.3,0.1

Type RM Length L Ch R = 1 ,7469.1  ,645,608.9,572.7
XS GIS Cut Line= 4
     1571356.776      251750.761     1570634.901      251589.476
      1570421.36       251462.74     1569340.992      251458.411
#Sta/Elev= 30
       0  932.07    38.9  933.26   126.5  927.74     292  909.54   408.8  888.66
   535.3  876.77   613.2  847.93   681.3  809.99   700.7  802.03   861.5  785.08
   882.9  784.59   911.6  784.51   930.7  788.23   959.3  803.07   978.4  810.64
  1017.5  820.44    1155   826.5  1213.9  833.31  1272.8  844.15  1321.9  857.95
  1400.5  884.72  1479.1  900.91  1616.6  936.68  1763.9  984.56  1891.6 1050.44
  1911.2 1058.56  1940.7 1066.54  1960.3 1068.98  2009.4 1060.19  2068.4 1055.76
#Mann= 3 , 0 , 0
       0     .05       0   861.5    .045       0   882.9     .08       0
Bank Sta=861.5,882.9
XS Rating Curve= 0 ,0
Exp/Cntr=0.3,0.1

Type RM Length L Ch R = 1 ,6860.2  ,1184.4,1218.2,1249.3
XS GIS Cut Line= 4
     1570874.846      250776.987     1570330.576      251026.987
     1570205.576      251248.341     1569408.701        251409.8
#Sta/Elev= 30
       0  964.46     108  945.94   166.9  932.61   294.6  895.35   392.8   868.8
   461.5  845.03   490.9  836.38   598.9  817.68   608.7  813.59   628.3  798.89
   657.6   794.3   692.3  784.83   696.7  783.84   707.3  783.99   804.3  793.22
   833.6  798.29   853.2  805.16   882.5   812.6   951.1  835.42  1039.3  861.24
  1156.8  899.76    1245  924.24    1294  935.48  1362.5  962.42  1450.7  989.35
  1538.9 1031.94  1597.6 1056.59  1617.2 1061.04    1627 1060.93  1666.2 1055.31
#Mann= 3 , 0 , 0
       0      .1       0   692.3    .045       0   707.3     .05       0
Bank Sta=692.3,707.3
XS Rating Curve= 0 ,0
Exp/Cntr=0.3,0.1

Type RM Length L Ch R = 1 ,5642    ,1415.6,1412.4,1405.9
XS GIS Cut Line= 5
     1571552.777      250569.186     1570561.034      250415.729
     1570088.338      250226.651     1569715.074      250083.422
     1568942.505      250092.102
#Sta/Elev= 30
       0  944.26   167.3  894.34   255.8  878.26   334.5  838.15   354.2  833.53
   373.9  834.06   423.1  846.01   472.3  852.13     551  885.53     610  900.87
   708.4  912.22   836.3   896.1  1179.8  828.94    1307  812.25    1356   810.6
  1434.3  794.63  1522.4     789  1717.4  785.03  1756.4  780.76  1766.2  779.96
  1775.9  780.07  1824.7  789.49    1893  816.42  1980.9   875.2  2147.2  961.21
  2264.5 1030.89  2352.6 1073.74  2460.1 1089.65  2518.8 1102.04  2685.1 1091.97
#Mann= 3 , 0 , 0
       0     .08       0  1756.4    .045       0  1775.9      .1       0
Bank Sta=1756.4,1775.9
XS Rating Curve= 0 ,0
Exp/Cntr=0.3,0.1

Type RM Length L Ch R = 1 ,4229.6  ,877.2,875.9,873.1
XS GIS Cut Line= 4
     1571599.456      249914.129     1571227.928      249653.713
     1570623.761      249553.018     1569839.039      249504.407
#Sta/Elev= 30
       0  967.22   106.2  943.34   212.4  913.11   241.3  900.01   366.8  872.17
   463.4  847.29   541.2  825.04   550.9  820.25   560.6  811.41   570.4  800.34
   580.1  791.35   589.8  787.35   599.5  785.35   619.9  776.03   628.7  774.46
   634.9  774.48   803.7  773.77   959.3   773.9   988.4   775.9   998.2   778.3
  1007.9  782.39  1066.2  811.38  1105.5  826.58  1498.6  951.77  1528.1  960.48
  1714.8 1008.41    1764 1023.78  1773.8 1025.43  1793.5 1025.82  1852.4  1020.5
#Mann= 3 , 0 , 0
       0     .07       0   619.9    .045       0   634.9     .05       0
Bank Sta=619.9,634.9
XS Rating Curve= 0 ,0
Exp/Cntr=0.3,0.1

Type RM Length L Ch R = 1 ,3353.7  ,612.2,612.2,610.7
XS GIS Cut Line= 4
     1571789.727      248950.609     1571164.727      248816.061
      1570743.72      248785.679     1569836.602      249206.686
#Sta/Elev= 30
       0  952.79     118  912.16   157.4  895.71   216.4  881.47   255.7  876.59
   275.4  872.14   344.2  852.22   383.6  843.56   413.1  834.17   472.1  824.92
   521.3  814.79   609.8   814.2   688.4  807.05   737.5  800.12     816  777.02
   874.9  768.72   894.5  769.36  1061.4  783.76  1071.2  786.44  1120.2  808.78
  1179.1  831.77  1198.7  838.67  1218.3  843.11    1434  860.68  1561.4  884.12
  1728.1   899.5  1806.6  910.68    1885  919.02  2012.4  926.14  2061.5  934.08
#Mann= 3 , 0 , 0
       0     .08       0   874.9    .045       0   894.5     .05       0
Bank Sta=874.9,894.5
XS Rating Curve= 0 ,0
Exp/Cntr=0.3,0.1

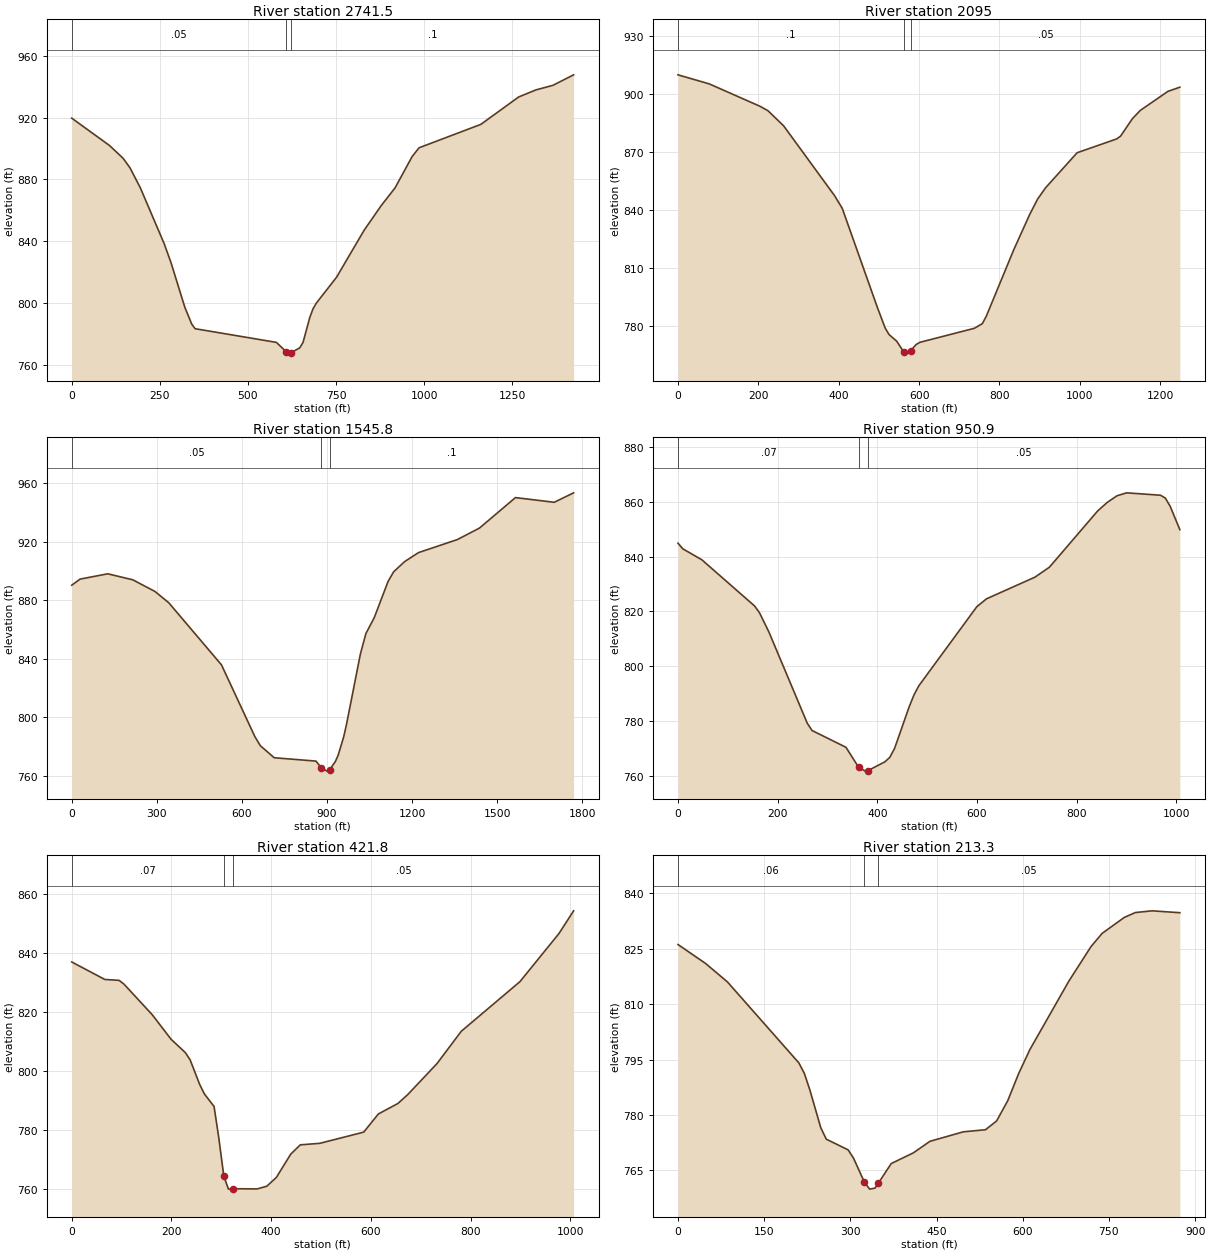
Type RM Length L Ch R = 1 ,2741.5  ,658.9,646.5,632.8
XS GIS Cut Line= 4
     1571609.872      248250.935     1571123.761      248254.407
      1570887.65       248243.99     1570189.734      248316.907
#Sta/Elev= 30
       0  919.72     107  902.03   145.8  893.69   165.3  887.52   194.4  874.67
   262.5  838.26     282  825.82   320.8  797.21   340.3  786.34     350  783.26
   580.7   774.4     609  768.24   618.5  767.43   622.7  767.77   646.8  770.82
   656.3  774.34   675.2   790.3   684.6  796.13   694.1  799.84   751.7  816.72
   829.7  847.07   878.4  863.11   917.4   874.5   966.1  894.89   985.6  900.52
    1161   915.7  1268.2  933.45    1317  938.02  1365.7  941.02  1424.2  947.81
#Mann= 3 , 0 , 0
       0     .05       0     609    .045       0   622.7      .1       0
Bank Sta=609,622.7
XS Rating Curve= 0 ,0
Exp/Cntr=0.3,0.1

Type RM Length L Ch R = 1 ,2095    ,537.8,549.2,560.9
XS GIS Cut Line= 4
     1571462.245      247575.052     1570985.683      247674.011
     1570811.204      247775.573     1570305.995      248017.761
#Sta/Elev= 30
       0  909.68    77.9  904.99   204.4  893.39   223.9  891.13   262.8  883.34
   389.4   847.3   408.8  840.66   496.3  789.39   515.6  778.79   525.2  775.44
   544.4  771.98   562.1766.3264   573.2  765.83  579.33767.1258   592.5  770.26
   602.1  771.42   737.8  778.68   757.4   781.1   767.2  784.89     836  819.47
   875.4  837.56     895  845.47   914.7  851.28   993.3  869.41  1091.6  876.54
  1101.4     878  1130.9  887.03  1150.6  891.31  1219.4  901.15  1248.9  903.28
#Mann= 3 , 0 , 0
       0      .1       0   562.1    .045       0  579.33     .05       0
Bank Sta=562.1,579.33
XS Rating Curve= 0 ,0
Exp/Cntr=0.3,0.1

Type RM Length L Ch R = 1 ,1545.8  ,584.8,594.9,604.5
XS GIS Cut Line= 4
     1571591.839      247246.269     1570878.269       247244.88
     1570574.449       247244.88     1569823.581      247275.262
#Sta/Elev= 30
       0  890.38    29.3  894.55   127.1  898.17     215  894.08   293.2  886.12
   342.1  878.36   527.8  835.93   645.2     787   664.7   780.7   713.6  772.47
   860.6  770.19   880.2  765.54   899.8  763.33   909.6  764.38   929.2  769.93
     939  774.22   958.6  786.84   968.4  795.27  1017.4  843.41  1036.9  857.43
  1066.2  868.19    1115  892.99  1134.5  899.53  1173.5  906.55  1222.3  912.67
    1359  921.56    1437  929.41  1563.9  950.25  1700.6  947.04  1768.9  953.51
#Mann= 3 , 0 , 0
       0     .05       0   880.2    .045       0   909.6      .1       0
Bank Sta=880.2,909.6
XS Rating Curve= 0 ,0
Exp/Cntr=0.3,0.1

Type RM Length L Ch R = 1 ,950.9   ,540.4,529.2,517.7
XS GIS Cut Line= 4
     1571315.168      246835.136      1571039.56      246750.501
     1570861.609      246670.206     1570338.605      246698.417
#Sta/Elev= 30
       0  844.89     9.6  842.84      48  838.82   153.8     822   163.4  819.61
   182.6  812.49   259.5   779.3   269.1  776.65   337.1  770.55   362.6  763.25
   376.2  761.86  381.22762.0365   415.2  765.25     425  766.84   434.7  770.12
     464  785.28   473.8  789.67   483.5  792.97   599.9  821.76   619.3  824.62
   716.3  832.49   745.4  836.11   842.4  856.63   861.8  859.76   881.2  862.15
   900.6  863.22   968.5  862.34   978.2   861.3   987.9  858.31  1007.3  849.81
#Mann= 3 , 0 , 0
       0     .07       0   362.6    .045       0  381.22     .05       0
Bank Sta=362.6,381.22
XS Rating Curve= 0 ,0
Exp/Cntr=0.3,0.1

Type RM Length L Ch R = 1 ,421.8   ,206.7,208.4,210.1
XS GIS Cut Line= 4
     1571394.762      246235.332     1571168.199      246211.894
     1570928.616      246230.123     1570394.762      246300.436
#Sta/Elev= 30
       0  837.06    66.4  831.12    94.9  830.82   104.4   829.6   161.3  819.17
   199.3   810.8   227.8  806.29   237.4  803.83   256.6  795.46   266.2   792.2
   285.4     788     295  777.22     305  764.29   314.3  759.93   323.9  760.07
   371.9     760   391.2  760.92   410.4  763.92   439.2  771.82   458.4  774.97
   497.4  775.48   585.5  779.28   614.9  785.45   654.1  789.01   673.6  791.99
   732.4  802.54   781.3  813.55   898.8  830.37   977.1  846.72  1006.5  854.43
#Mann= 3 , 0 , 0
       0     .07       0     305    .045       0   323.9     .05       0
Bank Sta=305,323.9
XS Rating Curve= 0 ,0
Exp/Cntr=0.3,0.1

Type RM Length L Ch R = 1 ,213.3   ,63.3,62.7,62.6
XS GIS Cut Line= 4
      1571364.38      246083.422     1571085.734      246015.714
     1570991.984      246015.714     1570502.401      246073.005
#Sta/Elev= 30
       0  826.17    47.8  821.06      86  816.04   210.3   794.1   219.8  791.28
   229.4  786.81   248.5  776.51   258.1  773.41   296.1  770.51   305.5  768.26
   324.3   761.8   333.6  759.87     343  760.15  348.42761.4128   371.1   766.8
   409.5  769.69   438.5  772.83   496.5   775.4   535.2  775.97   554.5  778.35
   573.8  783.81   593.1  791.27   612.5  797.72   680.1  816.21   718.8  825.61
   738.1  829.18   776.8  833.52   796.1  834.84   825.1   835.3   873.4  834.79
#Mann= 3 , 0 , 0
       0     .06       0   324.3    .045       0  348.42     .05       0
Bank Sta=324.3,348.42
XS Rating Curve= 0 ,0
Exp/Cntr=0.3,0.1

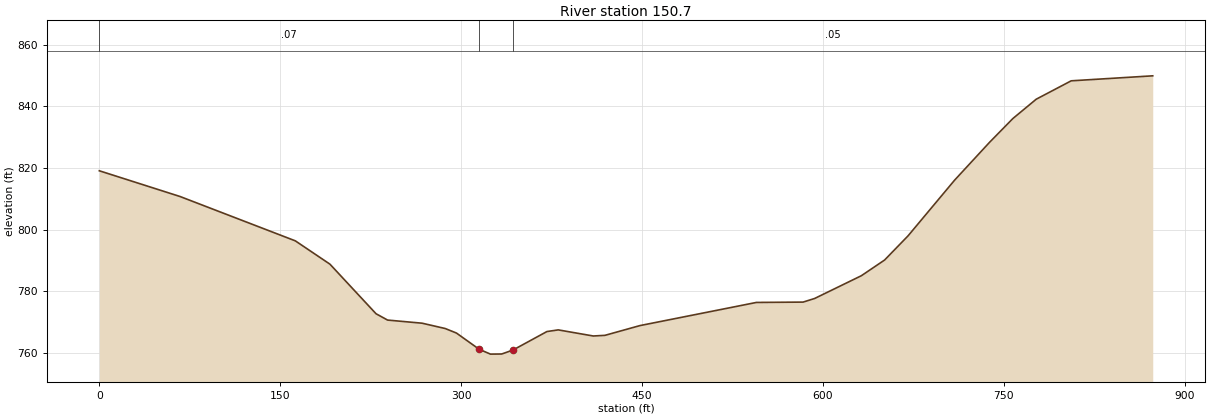
Type RM Length L Ch R = 1 ,150.7   ,136.7,150.7,162.9
XS GIS Cut Line= 4
     1571361.776      246020.922      1571083.13      245953.214
      1570989.38      245953.214     1570499.797      246010.505
#Sta/Elev= 30
       0  819.11    66.9  810.77   162.5  796.39   191.2  788.83   229.4  772.76
     239   770.7   267.6  769.69   286.8  767.96   296.1  766.49   314.9  761.24
   324.3  759.66   333.6   759.7     343  760.99   371.1  766.98   380.5  767.52
   409.5  765.54   419.2  765.75   448.2  768.91   544.8  776.42   583.5  776.53
   593.1  777.71   631.8  785.08   651.1  790.18   670.5     798   709.1  816.06
   738.1  828.34   757.4  836.04   776.8  842.32   805.8  848.28   873.4   849.9
#Mann= 3 , 0 , 0
       0     .07       0   314.9    .045       0     343     .05       0
Bank Sta=314.9,343
XS Rating Curve= 0 ,0
Exp/Cntr=0.3,0.1

Chan Stop Cuts=-1
Use User Specified Reach Order=0
Composite Channel Slope=5